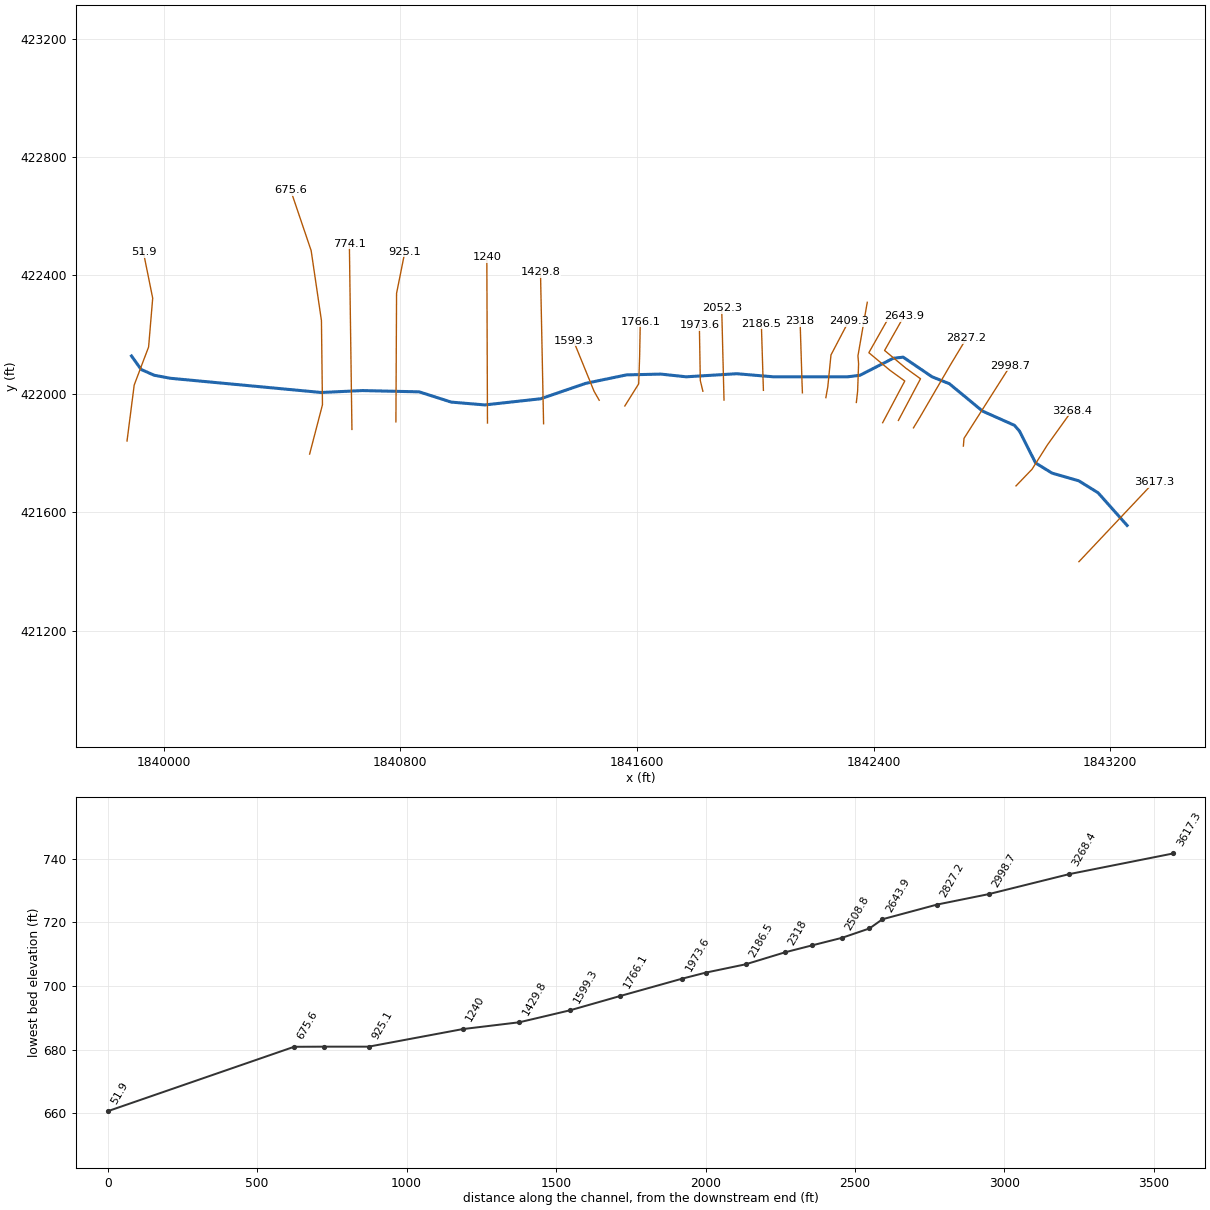
--- PAINTBRCH.prj (project) ---

Proj Title=PAINTBRCH
Current Plan=p01
Default Exp/Contr=0,0
English Units
Geom File=g01
Flow File=f01
Plan File=p01
BEGIN DESCRIPTION:
END DESCRIPTION:
DSS Export Rating Curves= 0
DSS Export Rating Curve Sorted= 0
DSS Export Volume Flow Curves= 0
DXF OffsetX= 0
DXF OffsetY= 0
DXF ScaleX= 0
DXF ScaleY= 0

--- PAINTBRCH.p01 (plan) ---

Plan Title=Floodplain
Program Version=4.00
Geom File=g01
Flow File=f01
K Sum by GR=0
Std Step Tol=0.01
Critical Tol=0.01
Num of Std Step Trials=20
Max Error Tol=0.3
Flow Tol Ratio=0.001
Split Flow NTrial=30
Split Flow Tol=0.02
Split Flow Ratio=0.02
Log Output Level=0
Friction Slope Method=1
Unsteady Friction Slope Method=2
Unsteady Bridges Friction Slope Method=1
Global Log Level=0
CheckData=False
Run HTab=0
Run UNet=0
Run PostProcess=0
UNET Theta=0
UNET Theta Warmup=0
UNET ZTol=0
UNET ZSATol=0
UNET MxIter=0
UNET MaxInSteps=0
UNET DtIC=0
UNET DtMin=0
UNET MaxCRTS=0
UNET WFStab=0
UNET SFStab=0
UNET WFX=0
UNET SFX=0
UNET DSS MLevel=0
UNET DZMax Abort=0
UNET Convert EG Bridges=0
UNET Use Existing IB Tables=0
UNET Froude Limit=0
UNET Froude Power=0
Write IC File=0
Echo Input=False
Echo Output=False
Write Detailed=0

--- PAINTBRCH.f01 (steady flow) ---

Flow Title=NFF Regression Equation
Program Version=4.10
Number of Profiles= 1
Profile Names=P100yr
River Rch & RM=PAINTBRCH,Main            ,3617.3
976.9805
River Rch & RM=PAINTBRCH,Main            ,2409.3
1032.684
Boundary for River Rch & Prof#=PAINTBRCH,Main            , 1
Up Type= 0
Dn Type= 3
Dn Slope=0.03
DSS Import GetInterval= 0
DSS Import GetPeak= 0
DSS Import FillOption= 0

--- PAINTBRCH.g01 (geometry) ---

Geom Title=USGS 10m DEM
Program Version=4.10

River Reach=PAINTBRCH       ,Main
Reach XY= 30
     1843256.745      421555.095     1843158.677      421665.411
     1843093.572      421705.776     1843002.839      421731.961
     1842947.545      421766.059     1842893.052      421873.744
     1842876.124      421893.276     1842768.052      421941.453
     1842656.072      422033.901     1842597.479      422057.338
     1842499.822      422123.744     1842465.968      422119.838
     1842353.989      422062.546     1842312.322      422057.338
      1842061.02      422057.338     1841937.322      422067.755
     1841766.749      422057.338     1841680.812      422066.453
     1841564.927      422063.849     1841426.906      422035.203
     1841274.562      421983.119      1841085.76      421962.286
     1840972.302      421971.854     1840864.167      422006.483
      1840672.11      422010.824     1840533.221      422004.314
     1840023.301      422052.332     1839968.572      422062.546
     1839924.302      422082.078     1839891.749      422127.651

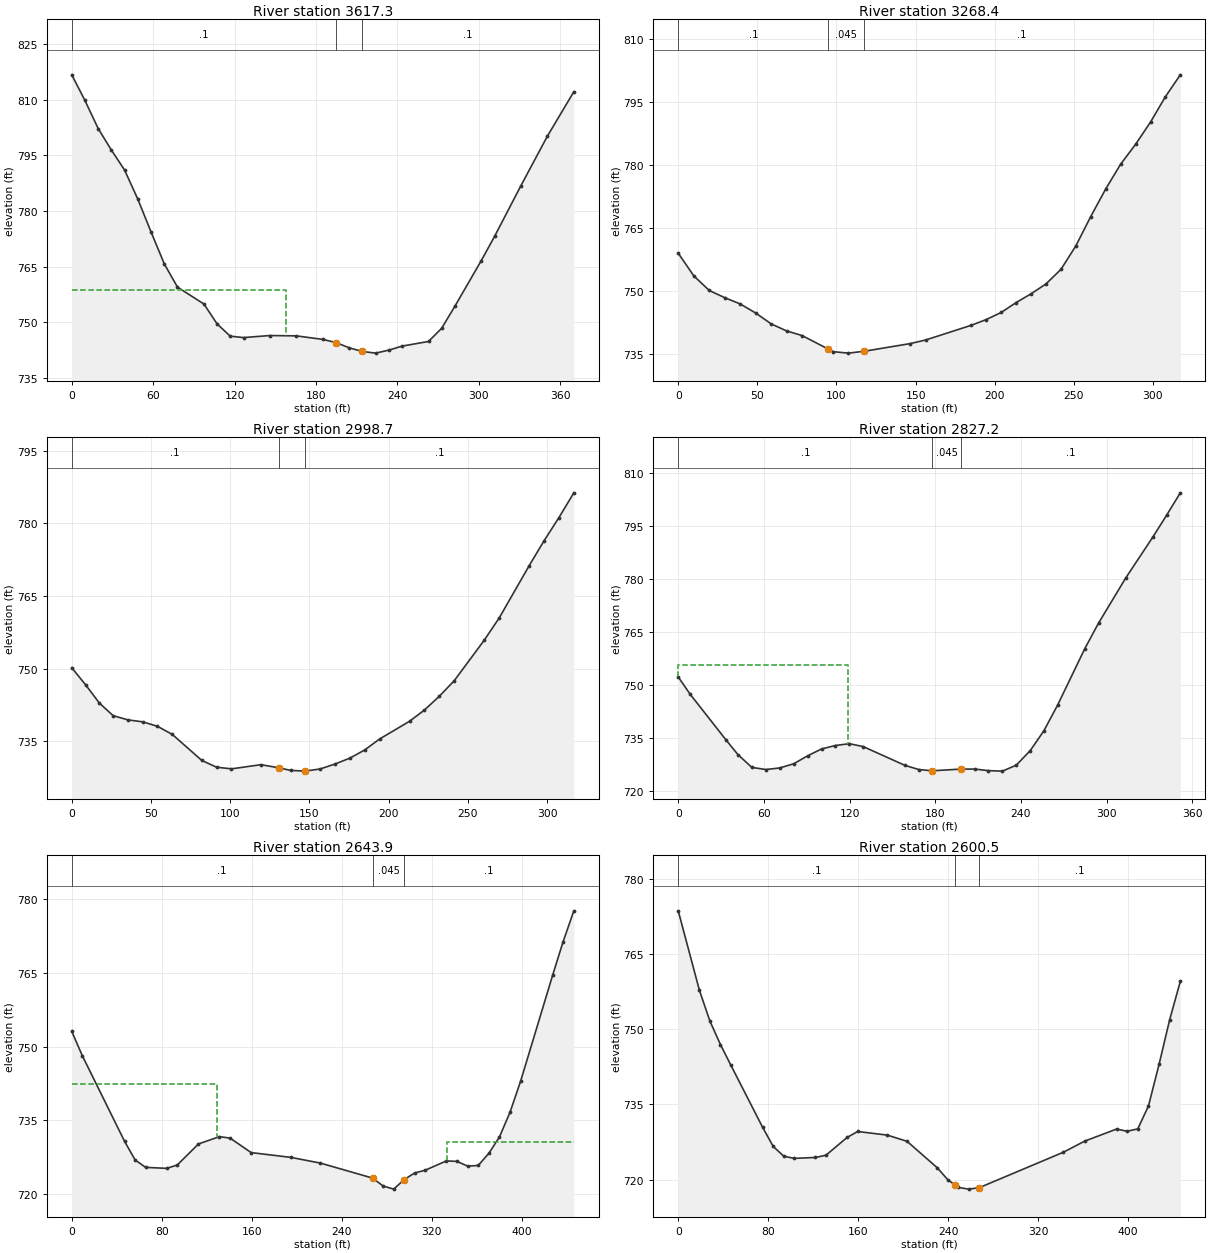
Type RM Length L Ch R = 1 ,3617.3  ,344.3,348.9,353.9
XS GIS Cut Line= 2
     1843093.977      421432.613     1843347.884       421701.71
#Sta/Elev= 30
       0  816.68     9.7  809.77    19.5  802.19    29.2  796.39    38.9  791.04
    48.7  783.16    58.4  774.36    68.2  765.73    77.9  759.48    97.4  754.92
   107.1  749.56   116.8  746.26   126.6  745.88     146  746.43   165.5  746.34
     185  745.39   194.7  744.54   204.5  743.11   214.2  742.14   223.9  741.69
   233.7   742.5   243.4  743.58   262.9  744.83   272.6  748.39   282.4  754.37
   301.8  766.63   311.6  773.16     331  786.81   350.5  800.15     370  812.13
#Mann= 3 , 0 , 0
       0      .1       0   194.7    .045       0   214.2      .1       0
#XS Ineff= 2 , 0
          157.66  758.57
Permanent Ineff=
       F       F
Bank Sta=194.7,214.2
XS Rating Curve= 0 ,0
Exp/Cntr=0.3,0.1

Type RM Length L Ch R = 1 ,3268.4  ,269.6,269.7,268.6
XS GIS Cut Line= 4
     1842881.304      421688.689     1842935.557      421745.113
     1842987.641      421827.578     1843070.106      421942.596
#Sta/Elev= 30
       0  758.96     9.8  753.58    19.6  750.08    29.4  748.37    39.1  746.89
    48.9  744.73    58.7  742.14    68.5  740.45    78.3  739.35    94.9  736.11
    97.8  735.52   107.5  735.17   117.3   735.6   146.6  737.44   156.3  738.29
   185.2   741.8   194.7  743.17   204.1  744.85   213.6  747.22     223   749.3
   232.4  751.64   241.9  755.12   251.3  760.71   260.7  767.69   270.2  774.28
   279.6  780.15     289  784.86   298.5  790.19   307.9  796.22   317.3  801.42
#Mann= 3 , 0 , 0
       0      .1       0    94.9    .045       0   117.3      .1       0
Bank Sta=94.9,117.3
XS Rating Curve= 0 ,0
Exp/Cntr=0.3,0.1

Type RM Length L Ch R = 1 ,2998.7  ,170.7,171.5,172.4
XS GIS Cut Line= 4
     1842703.352      421823.238     1842705.523       421849.28
     1842785.818      421975.148     1842861.773      422094.505
#Sta/Elev= 30
       0  750.19     8.7   746.7    17.4  742.92    26.1  740.32    35.5  739.44
    44.8  739.04    54.1  738.12    63.5  736.43    82.1  731.07    91.4  729.68
   100.8  729.34   119.4   730.2   130.5  729.57   138.1  729.02   147.4  728.87
   156.8  729.32   166.1  730.33   175.4  731.53   184.9  733.24   194.3   735.5
   213.2  739.16   222.6  741.48     232  744.32   241.4  747.53   260.3  755.87
   269.8  760.49   288.6  771.21     298  776.35   307.5   781.2   316.9   786.3
#Mann= 3 , 0 , 0
       0      .1       0   130.5    .045       0   147.4      .1       0
Bank Sta=130.5,147.4
XS Rating Curve= 0 ,0
Exp/Cntr=0.3,0.1

Type RM Length L Ch R = 1 ,2827.2  ,146.7,183.3,216.6
XS GIS Cut Line= 4
     1842534.733       421884.87     1842556.434      421920.677
     1842659.516      422097.544     1842713.769      422187.604
#Sta/Elev= 30
       0  752.29     8.4  747.37    33.5  734.43    41.9  730.25    51.6  726.66
    61.4  726.06    71.1  726.51    80.9   727.7    90.6  729.94   100.4   731.9
   110.1  732.87   119.9  733.38   129.6  732.56   158.8  727.24   168.6  726.05
   178.1  725.71   197.8  726.18   207.6   726.2   217.3  725.75   227.1  725.61
   236.8   727.3   246.6  731.44   256.1  737.02   265.7  744.28   284.8  760.31
   294.4  767.53   313.5  780.35   332.6  792.01   342.2  798.17   351.7  804.45
#Mann= 3 , 0 , 0
       0      .1       0   178.1    .045       0   197.8      .1       0
#XS Ineff= 2 , 0
          118.69  755.59
Permanent Ineff=
       F       F
Bank Sta=178.1,197.8
XS Rating Curve= 0 ,0
Exp/Cntr=0.3,0.1

Type RM Length L Ch R = 1 ,2643.9  ,46.7,43.4,42.2
XS GIS Cut Line= 5
     1842483.734      421909.827     1842558.469      422050.699
     1842508.691      422086.693     1842437.076      422146.372
     1842502.181      422261.389
#Sta/Elev= 30
       0  753.09     9.4  748.14    46.9  730.73    56.3  726.92    65.7  725.41
    84.4  725.21    93.8   725.9   112.6  730.18   131.3  731.67   140.7  731.37
   159.5  728.42   194.6  727.45   220.9  726.29   267.5  723.22   276.8  721.61
   286.2  720.98   295.5  722.93   304.8  724.27   314.1  724.82     333  726.73
   342.4  726.63   351.9  725.66   361.3   725.8   370.8  728.28   380.2  731.62
   389.6  736.65   399.1  743.05   427.4  764.51   436.8   771.4   446.3  777.66
#Mann= 3 , 0 , 0
       0      .1       0   267.5    .045       0   295.5      .1       0
#XS Ineff= 2 , 0
          128.88  742.42  333.92          730.64
Permanent Ineff=
       F       F
Bank Sta=267.5,295.5
XS Rating Curve= 0 ,0
Exp/Cntr=0.3,0.1

Type RM Length L Ch R = 1 ,2600.5  ,113.1,91.8,71.3
XS GIS Cut Line= 5
     1842430.566      421902.231     1842505.301      422043.104
     1842455.523      422079.097     1842383.908      422138.776
     1842449.012      422253.794
#Sta/Elev= 30
       0  773.57    18.8  757.75    28.1  751.62    37.5  746.92    46.9  742.74
      75  730.42    84.4  726.61    93.8  724.65   103.2  724.22     122   724.4
   131.3  724.85   150.1  728.39   159.5  729.58   185.8  728.86   203.4  727.62
   230.2  722.36   239.5  719.99     246  718.91   248.9  718.43   258.2  718.09
   267.5  718.37   342.4  725.45   361.3  727.66   389.6  730.06   399.1  729.63
   408.5   730.1     418  734.67   427.4  742.95   436.8  751.83   446.3   759.5
#Mann= 3 , 0 , 0
       0      .1       0     246    .045       0   267.5      .1       0
Bank Sta=246,267.5
XS Rating Curve= 0 ,0
Exp/Cntr=0.3,0.1

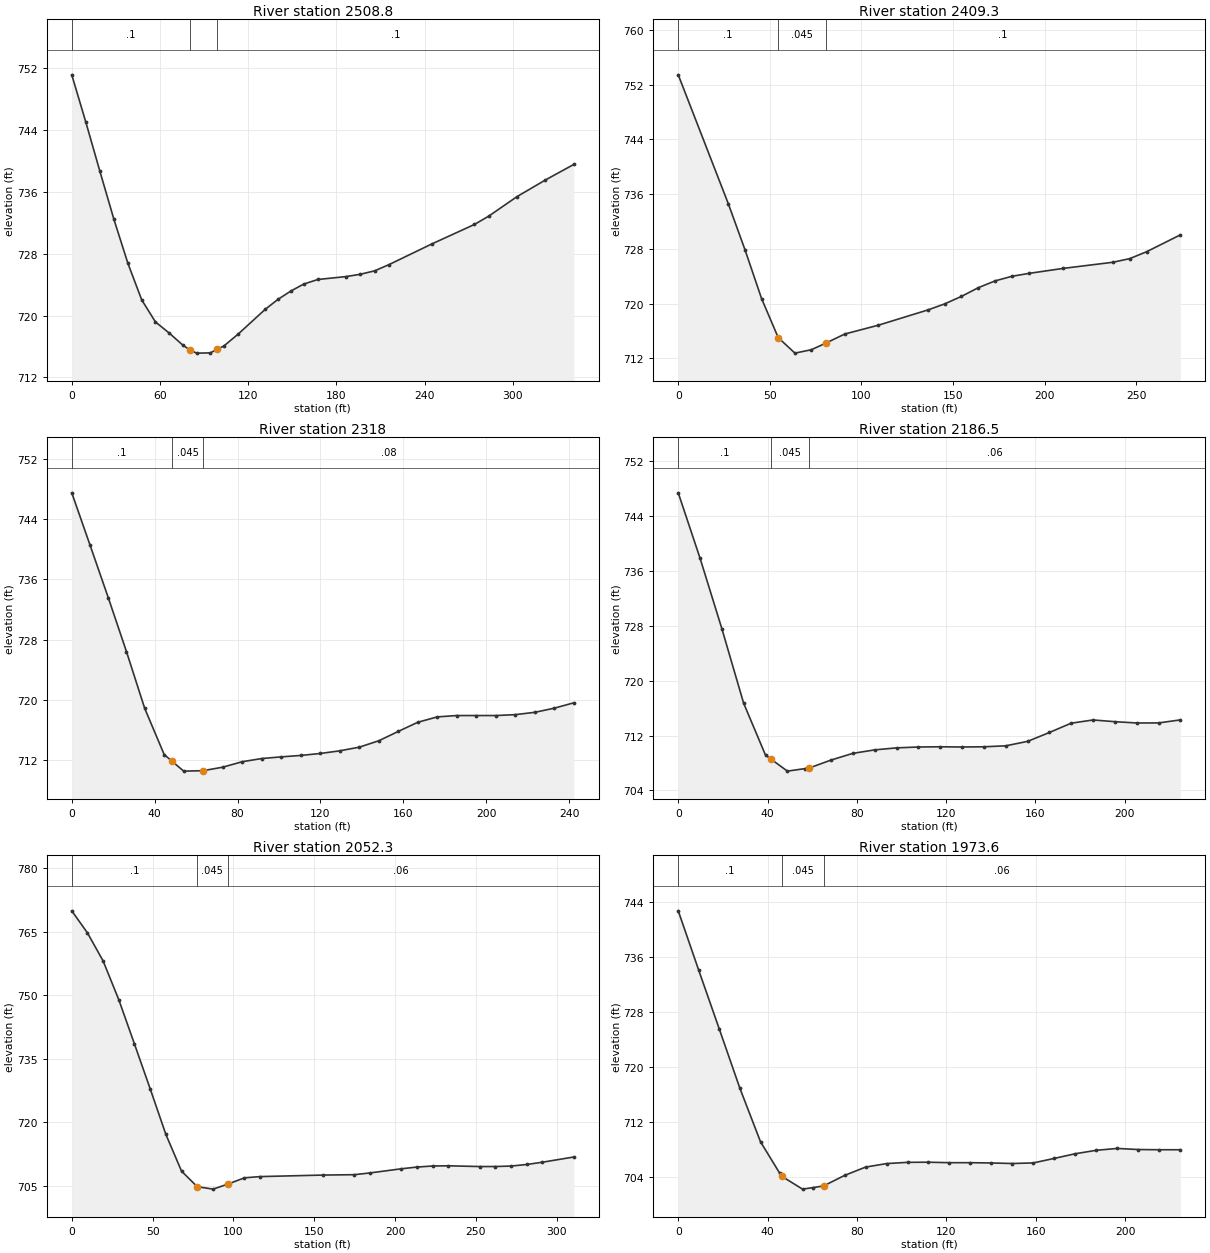
Type RM Length L Ch R = 1 ,2508.8  ,100.9,99.4,98
XS GIS Cut Line= 5
      1842341.59       421970.59     1842345.931      422008.568
     1842349.186      422101.884     1842347.016      422127.925
     1842378.483      422309.132
#Sta/Elev= 30
       0  751.12     9.6  744.98    19.1  738.67    28.7  732.42    38.2  726.74
    47.6  722.02    56.9  719.18    66.2  717.75    75.6  716.17   80.29  715.56
    84.9  715.14    94.2  715.17      99  715.63   103.6  716.08   112.9  717.55
   131.6   720.8   140.3  722.09     149  723.16   157.7  724.06   167.4  724.66
   186.8  725.04   196.4  725.34   206.1  725.78   215.8  726.58   244.8  729.24
   273.9  731.77   283.6  732.84   302.9  735.37   322.3  737.53   341.6  739.54
#Mann= 3 , 0 , 0
       0      .1       0   80.29    .045       0      99      .1       0
Bank Sta=80.29,99
XS Rating Curve= 0 ,0
Exp/Cntr=0.3,0.1

Type RM Length L Ch R = 1 ,2409.3  ,88.3,91.3,94.3
XS GIS Cut Line= 4
     1842238.509      421986.866     1842245.019      422022.674
      1842255.87      422131.181     1842315.549      422245.113
#Sta/Elev= 22
       0  753.45    27.3  734.64    36.4  727.92    45.5  720.75    54.6  715.04
    63.7  712.78    72.7  713.28    80.4  714.22    90.9  715.57   109.1  716.85
   136.4   719.1   145.4  719.97   154.6  721.07   163.8  722.34     173  723.34
   182.2  724.01   191.4  724.43   209.8  725.15   237.3  726.06   246.5  726.59
   255.7   727.6   274.1  730.06
#Mann= 3 , 0 , 0
       0      .1       0    54.6    .045       0    80.4      .1       0
Bank Sta=54.6,80.4
XS Rating Curve= 0 ,0
Exp/Cntr=0.3,0.1

Type RM Length L Ch R = 1 ,2318    ,131.5,131.6,131.5
XS GIS Cut Line= 3
     1842159.313      422003.099     1842158.011      422038.255
     1842151.501      422245.287
#Sta/Elev= 28
       0  747.48     8.8  740.56    17.6  733.59    26.4  726.43    35.2   718.9
    44.6  712.78    48.4  711.89      54  710.58    63.4  710.64    72.8   711.1
    82.3  711.83    91.7  712.25   101.1  712.47   110.5  712.66   119.9  712.92
   129.3  713.27   138.8  713.76   148.2  714.61   157.6  715.85     167  717.06
   176.4  717.77   185.8  717.95   195.2  717.95   204.6  717.95   214.1  718.07
   223.5  718.38   232.9  718.93   242.3  719.64
#Mann= 3 , 0 , 0
       0      .1       0    48.4    .045       0    63.4     .08       0
Bank Sta=48.4,63.4
XS Rating Curve= 0 ,0
Exp/Cntr=0.3,0.1

Type RM Length L Ch R = 1 ,2186.5  ,134.3,134.2,134.1
XS GIS Cut Line= 2
     1842027.484      422011.577      1842020.54      422236.404
#Sta/Elev= 26
       0  747.39     9.8  737.83    19.6  727.52    29.3  716.71    39.1  709.14
    41.6  708.55    48.9  706.81    56.6  707.17    58.7  707.27    68.5  708.43
    78.2   709.4      88  709.91    97.8   710.2   107.6  710.33   117.4  710.36
   127.1  710.33   136.9  710.36   146.7   710.5   156.5  711.15   166.3  712.45
     176   713.8   185.8  714.27   195.6  714.02   205.4  713.83   215.2  713.84
   224.9  714.28
#Mann= 3 , 0 , 0
       0      .1       0    41.6    .045       0    58.7     .06       0
Bank Sta=41.6,58.7
XS Rating Curve= 0 ,0
Exp/Cntr=0.3,0.1

Type RM Length L Ch R = 1 ,2052.3  ,77.4,78.7,78.5
XS GIS Cut Line= 2
     1841894.325      421978.837     1841886.527       422289.34
#Sta/Elev= 26
       0   769.9     9.7  764.69    19.4  758.06    29.1   748.9    38.8  738.44
    48.5  727.88    58.2  717.12    67.9  708.43    77.6  704.76    87.4  704.18
    96.4  705.34   106.8  706.85   116.5  707.14   155.3   707.5   174.7  707.59
   184.4     708   203.8  708.98   213.5  709.39   223.2  709.64     233  709.69
   252.4  709.51   262.1  709.52   271.8  709.63   281.5     710   291.2  710.54
   310.6  711.77
#Mann= 3 , 0 , 0
       0      .1       0    77.6    .045       0    96.4     .06       0
Bank Sta=77.6,96.4
XS Rating Curve= 0 ,0
Exp/Cntr=0.3,0.1

Type RM Length L Ch R = 1 ,1973.6  ,210.2,207.5,206.4
XS GIS Cut Line= 3
     1841822.927      422008.568     1841814.247      422044.375
     1841810.991      422232.092
#Sta/Elev= 27
       0   742.7     9.2  734.04    18.4   725.5    27.6  716.91    36.8  709.16
    45.4  704.59    46.2  704.17    55.6  702.28    60.4  702.51      65  702.74
    74.4  704.27    83.8  705.48    93.2  705.99   102.6  706.17   111.9  706.19
   121.3  706.12   130.7  706.12   140.1  706.08   149.5     706   158.9  706.09
   168.3  706.75   177.6  707.42     187  707.92   196.4  708.19   205.8  708.03
   215.2     708   224.6     708
#Mann= 3 , 0 , 0
       0      .1       0    46.2    .045       0      65     .06       0
Bank Sta=46.2,65
XS Rating Curve= 0 ,0
Exp/Cntr=0.3,0.1

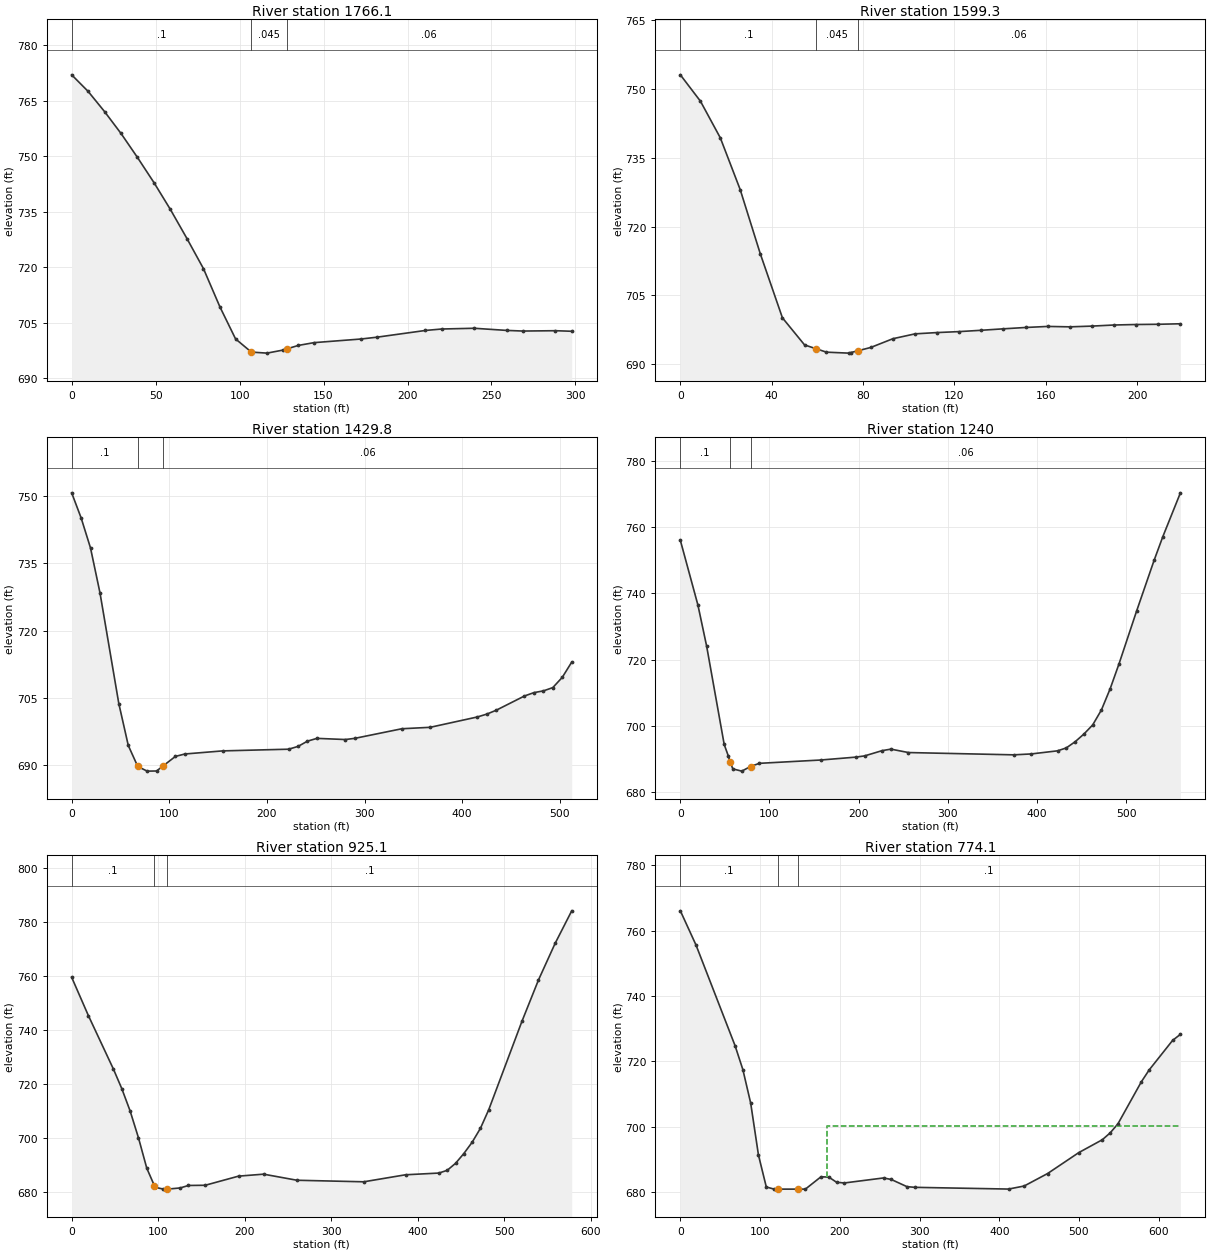
Type RM Length L Ch R = 1 ,1766.1  ,157.2,166.8,176.3
XS GIS Cut Line= 4
     1841559.038      421958.727     1841605.913      422033.524
     1841609.168       422126.84     1841611.339      422242.943
#Sta/Elev= 26
       0  771.93     9.8  767.46    19.6     762    29.4   756.1    39.2  749.62
      49  742.85    58.8  735.59    68.7  727.71    78.5  719.61    88.3  709.29
    97.6  700.66     107   697.1   116.3  696.82   125.6  697.62     128  697.95
     135   698.9   144.3  699.65   172.3  700.63   181.6  701.11   210.7  702.94
   220.4  703.33   239.7  703.53   259.1  702.95   268.7  702.78   288.1  702.87
   297.8  702.72
#Mann= 3 , 0 , 0
       0      .1       0     107    .045       0     128     .06       0
Bank Sta=107,128
XS Rating Curve= 0 ,0
Exp/Cntr=0.3,0.1

Type RM Length L Ch R = 1 ,1599.3  ,177.8,169.5,161
XS GIS Cut Line= 3
      1841472.45      421978.186     1841455.089      422008.568
     1841385.644      422178.924
#Sta/Elev= 27
       0  753.12     8.8  747.36    17.5  739.36    26.2  728.07      35  714.06
    44.7  700.06    54.4  694.14    59.6  693.28      64  692.56    73.7  692.35
    74.6  692.47   77.72  692.86    83.4  693.59    93.1   695.5   102.8  696.56
   112.4  696.84   122.1  697.05   131.8  697.34   141.5  697.66   151.2  697.95
   160.9  698.18   170.6  698.09   180.2  698.25   189.9  698.49   199.6   698.6
   209.3  698.65     219  698.76
#Mann= 3 , 0 , 0
       0      .1       0    59.6    .045       0   77.72     .06       0
Bank Sta=59.6,77.72
XS Rating Curve= 0 ,0
Exp/Cntr=0.3,0.1

Type RM Length L Ch R = 1 ,1429.8  ,190.1,189.8,189.6
XS GIS Cut Line= 2
     1841284.487      421898.788      1841274.07      422410.941
#Sta/Elev= 30
       0  750.76     9.7  745.15    19.3  738.44      29  728.42    48.3  703.67
      58  694.31    67.7  689.62    77.3  688.58      87  688.61      94   689.8
   106.3  691.87     116  692.41   154.6   693.1   222.3  693.48     232  694.11
   241.6  695.28   251.3   695.9   280.3  695.64     290   695.9   338.3  698.05
   367.3  698.37   415.6  700.68   425.3  701.32   434.9  702.18   463.9  705.37
   473.6  706.12   483.3  706.51   492.9  707.24   502.6  709.53   512.3  712.94
#Mann= 3 , 0 , 0
       0      .1       0    67.7    .045       0      94     .06       0
Bank Sta=67.7,94
XS Rating Curve= 0 ,0
Exp/Cntr=0.3,0.1

Type RM Length L Ch R = 1 ,1240    ,315,314.8,314.7
XS GIS Cut Line= 2
     1841094.845      421901.146     1841092.675      422462.127
#Sta/Elev= 30
       0  755.99    19.7  736.49    29.5  724.08    49.2  694.46      54  690.85
    55.8  689.06      59  687.09    68.9  686.43    78.7  687.82    88.6  688.78
   157.5  689.78   196.8  690.65   206.7  691.02   226.4  692.61   236.2  693.06
   255.9  692.03     374  691.34   393.7  691.61   423.2  692.55     433  693.43
   442.9  695.29   452.7   697.6   462.6  700.36   472.4  704.88   482.2  711.27
   492.1  718.75   511.8  734.64   531.5  749.98   541.3  757.12     561  770.31
#Mann= 3 , 0 , 0
       0      .1       0    55.8    .045       0    78.7     .06       0
Bank Sta=55.8,78.7
XS Rating Curve= 0 ,0
Exp/Cntr=0.3,0.1

Type RM Length L Ch R = 1 ,925.1   ,150.6,151,151.5
XS GIS Cut Line= 3
     1840785.384      421905.125     1840787.554      422339.152
     1840815.766      422480.211
#Sta/Elev= 30
       0  759.47    19.3  745.28    48.2  725.46    57.9   718.2    67.5  709.94
    77.2  699.94    86.8  688.66    95.6  682.18    96.4  681.59   106.1   680.9
   110.6   680.9   125.4  681.34     135  682.26   154.3  682.33   192.9  685.72
   221.8  686.45   260.4  684.19   337.6  683.62   385.8  686.22   424.4  686.86
     434  687.88   443.6  690.46   453.2  694.09   462.8  698.28   472.4  703.46
     482  710.36   520.3  743.09   539.5   758.5   558.7  772.05   577.9  784.13
#Mann= 3 , 0 , 0
       0      .1       0    95.6    .045       0   110.6      .1       0
Bank Sta=95.6,110.6
XS Rating Curve= 0 ,0
Exp/Cntr=0.3,0.1

Type RM Length L Ch R = 1 ,774.1   ,98.5,98.4,98.4
XS GIS Cut Line= 2
     1840636.729      421879.517     1840628.049      422506.687
#Sta/Elev= 30
       0  766.08    19.6  755.63    68.6  724.82    78.4  717.49    88.2  707.24
      98  691.28   107.8  681.56   117.6   680.9   122.1   680.9     147   680.9
   156.8   680.9   176.4  684.68   186.2  684.58     196  682.99   205.8  682.79
   254.8  684.32   264.6  683.85   284.2  681.66     294  681.45   411.6  680.92
   431.2  681.85   460.6  685.67   499.8  692.09   529.2  696.01     539  698.09
   548.8  700.87   578.2  713.75     588  717.38   617.4  726.42   627.2  728.28
#Mann= 3 , 0 , 0
       0      .1       0   122.1    .045       0     147      .1       0
#XS Ineff= 2 , 0
                          183.53          700.28
Permanent Ineff=
       F       F
Bank Sta=122.1,147
XS Rating Curve= 0 ,0
Exp/Cntr=0.3,0.1

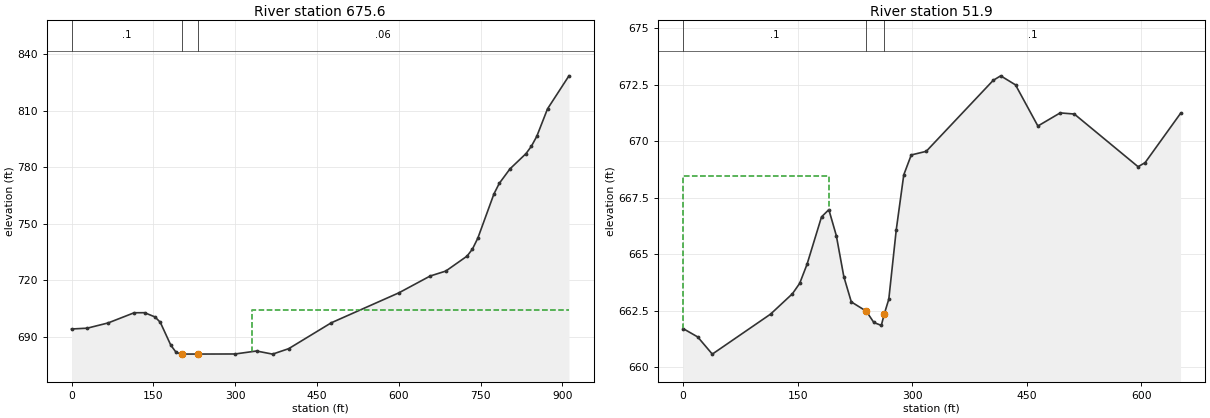
Type RM Length L Ch R = 1 ,675.6   ,631.5,623.7,616.7
XS GIS Cut Line= 5
     1840493.717      421796.111      1840537.12      421962.778
     1840533.648        422247.5     1840498.925      422483.611
     1840429.481      422688.472
#Sta/Elev= 30
       0  694.21    28.7  694.64      67  697.42   114.8  702.83     134  702.86
   153.1   700.6   162.7  697.77     182   685.6   191.9  681.73   201.7   680.9
   231.1   680.9   299.9  680.94   339.1  682.52   368.6  680.86   398.1  683.76
   476.1  697.49   600.2  713.43   657.4  722.34   686.1  724.97   725.1  732.92
     735  736.68   744.8  742.43   774.3  765.89   784.1  771.53   803.8  779.26
   833.3   787.4   843.1  791.32   852.9  796.52   872.6  811.13   911.9  828.67
#Mann= 3 , 0 , 0
       0      .1       0   201.7    .045       0   231.1     .06       0
#XS Ineff= 2 , 0
                          330.38          704.29
Permanent Ineff=
       F       F
Bank Sta=201.7,231.1
XS Rating Curve= 0 ,0
Exp/Cntr=0.3,0.1

Type RM Length L Ch R = 1 ,51.9    ,66.2,51.9,36.9
XS GIS Cut Line= 5
      1839876.53      421840.382     1839900.835      422029.618
     1839949.446       422158.09     1839963.335      422323.021
     1839932.085      422477.535
#Sta/Elev= 30
       0  661.72    19.1  661.35    38.2  660.59   114.5  662.36   143.1  663.26
   152.6  663.72   162.2  664.56   181.2  666.66   190.8  666.98   200.6  665.83
   210.4  664.02   220.2   662.9   239.8  662.49   249.7  661.99   259.5  661.86
  263.51  662.38   269.3  663.02   279.1   666.1   288.9  668.52   298.7   669.4
   318.3  669.56     406   672.7   415.8   672.9   435.2   672.5   464.5  670.68
   493.7  671.26   512.2  671.21   595.7  668.88   604.9  669.06   651.3  671.24
#Mann= 3 , 0 , 0
       0      .1       0   239.8    .045       0  263.51      .1       0
#XS Ineff= 2 , 0
          190.35  668.45
Permanent Ineff=
       F       F
Bank Sta=239.8,263.51
XS Rating Curve= 0 ,0
Exp/Cntr=0.3,0.1

Chan Stop Cuts=-1
Use User Specified Reach Order=0
Composite Channel Slope=5